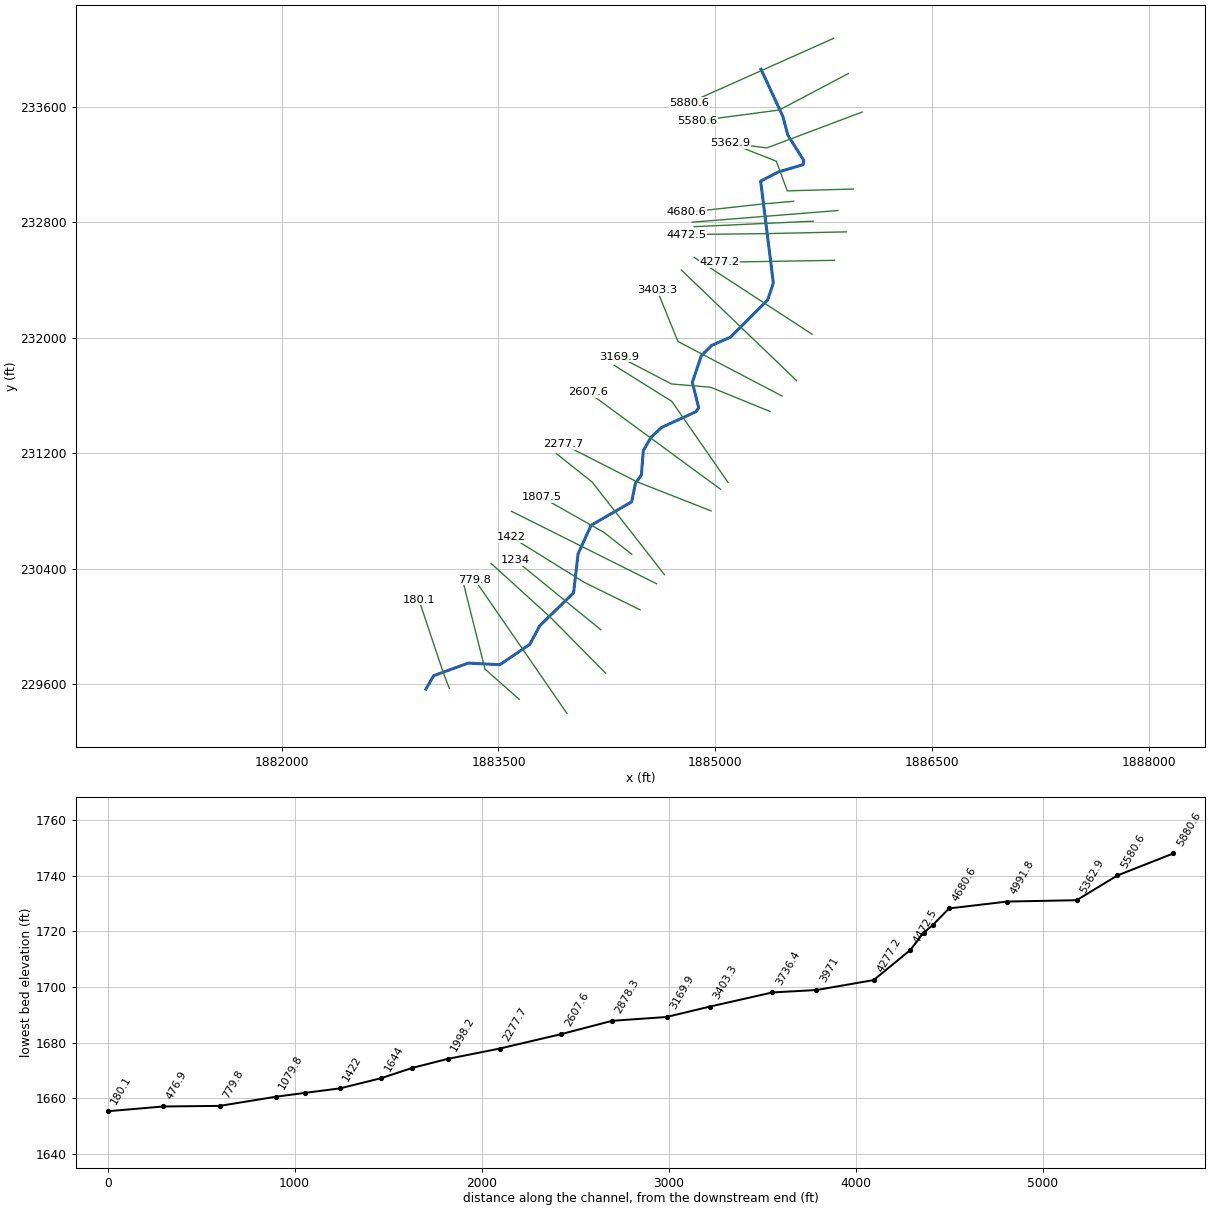
--- RffBrnch.prj (project) ---

Proj Title=RffBrnch
Current Plan=p01
Default Exp/Contr=0,0
English Units
Geom File=g01
Flow File=f01
Plan File=p01
BEGIN DESCRIPTION:
END DESCRIPTION:
DSS Export Rating Curves= 0
DSS Export Rating Curve Sorted= 0
DSS Export Volume Flow Curves= 0
DXF OffsetX= 0
DXF OffsetY= 0
DXF ScaleX= 0
DXF ScaleY= 0

--- RffBrnch.p01 (plan) ---

Plan Title=Floodplain
Program Version=4.00
Geom File=g01
Flow File=f01
K Sum by GR=0
Std Step Tol=0.01
Critical Tol=0.01
Num of Std Step Trials=20
Max Error Tol=0.3
Flow Tol Ratio=0.001
Split Flow NTrial=30
Split Flow Tol=0.02
Split Flow Ratio=0.02
Log Output Level=0
Friction Slope Method=1
Unsteady Friction Slope Method=2
Unsteady Bridges Friction Slope Method=1
Global Log Level=0
CheckData=False
Run HTab=0
Run UNet=0
Run PostProcess=0
UNET Theta=0
UNET Theta Warmup=0
UNET ZTol=0
UNET ZSATol=0
UNET MxIter=0
UNET MaxInSteps=0
UNET DtIC=0
UNET DtMin=0
UNET MaxCRTS=0
UNET WFStab=0
UNET SFStab=0
UNET WFX=0
UNET SFX=0
UNET DSS MLevel=0
UNET DZMax Abort=0
UNET Convert EG Bridges=0
UNET Use Existing IB Tables=0
UNET Froude Limit=0
UNET Froude Power=0
Write IC File=0
Echo Input=False
Echo Output=False
Write Detailed=0

--- RffBrnch.f01 (steady flow) ---

Flow Title=NFF Regression Equation
Program Version=4.00
Number of Profiles=1
Profile Names=P100yr
River Rch & RM=RffBrnch,Main      ,5880.6
843.1968
River Rch & RM=RffBrnch,Main      ,5362.9
849.3299
River Rch & RM=RffBrnch,Main      ,4991.8
1082.475
River Rch & RM=RffBrnch,Main      ,3971
1117.592
River Rch & RM=RffBrnch,Main      ,180.1
1219.906
Boundary for River Rch & Prof#=RffBrnch,Main      ,1
Up Type=0
Dn Type=3
Dn Slope=0.006306

--- RffBrnch.g01 (geometry) ---

Geom Title=USGS 3m DEM
Program Version=4.10

River Reach=RffBrnch        ,Main
Reach XY= 30
     1885315.055      233860.038     1885467.194      233530.714
     1885500.397      233403.738     1885611.014      233228.231
     1885606.927      233198.676     1885436.562       233148.44
     1885312.817      233084.619     1885400.347      232379.047
     1885361.896       232261.31     1885104.367      232003.506
     1884974.109      231946.198     1884902.281      231874.362
     1884840.558      231689.052     1884884.387        231513.7
     1884864.677        231486.4      1884628.91      231378.297
     1884555.391      231310.542     1884501.253      231216.785
     1884488.221      231049.405     1884446.537      230988.839
     1884420.846      230862.425     1884140.425      230699.683
     1884050.541      230503.001     1884019.018      230231.819
       1883784.8      230002.829     1883717.062      229875.181
     1883509.065      229733.576     1883291.121      229744.942
     1883051.447       229657.68     1882997.827      229563.841

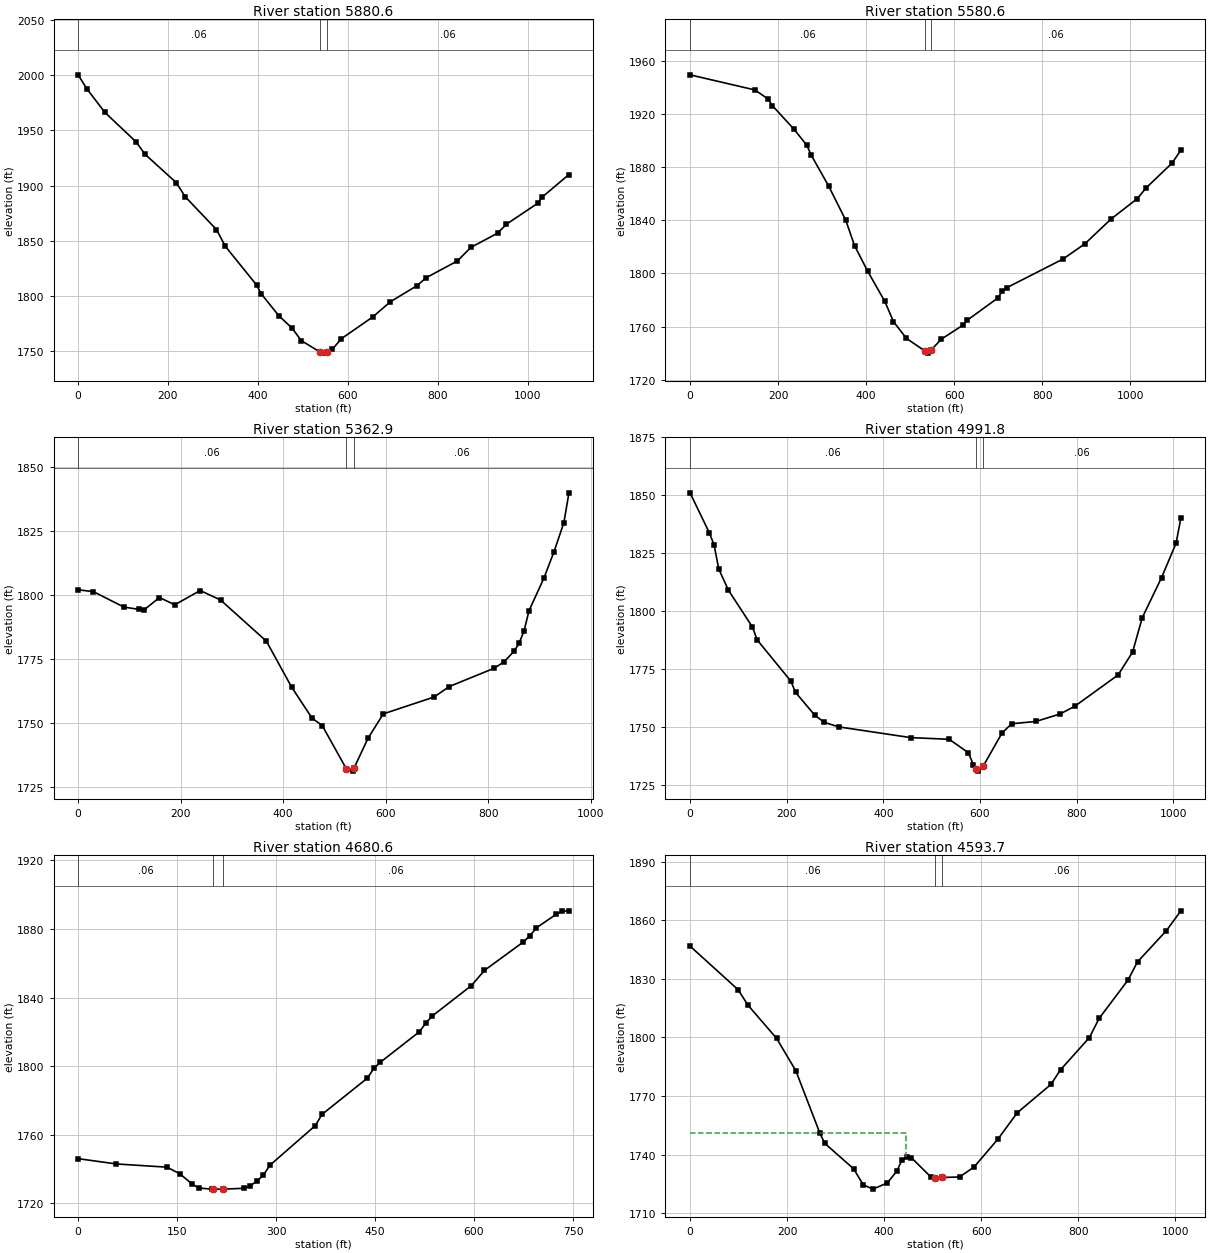
Type RM Length L Ch R = 1 ,5880.6  ,298.5,300,293.4
XS GIS Cut Line= 3
     1885817.553      234073.842     1885319.138      233850.909
     1884820.723      233627.977
#Sta/Elev= 30
       0 2000.43    19.8 1987.57    59.6 1966.39     129 1939.65   148.9 1928.44
   218.4 1902.68   238.2 1889.95   307.8 1860.16   327.6 1844.94   397.1 1809.87
     407 1802.09   446.7 1781.96   476.5 1770.61   496.4 1759.49   538.5 1749.06
     546 1748.11   553.5 1748.72   565.8 1751.66   585.7 1761.16   655.2 1780.82
   694.9 1794.71   754.5 1809.41   774.3 1816.47   843.8 1831.65   873.6 1843.91
   933.2 1856.84     953    1865  1022.5 1883.98  1032.4 1889.54    1092 1910.04
#Mann= 3 , 0 , 0
       0     .06       0   538.5    .045       0   553.5     .06       0
Bank Sta=538.5,553.5
XS Rating Curve= 0 ,0
Exp/Cntr=0.3,0.1

Type RM Length L Ch R = 1 ,5580.6  ,220.4,217.5,222.8
XS GIS Cut Line= 3
     1885919.446      233829.844     1885441.129      233577.055
     1884871.806      233501.718
#Sta/Elev= 30
       0 1949.25   147.6 1937.87   177.1 1931.13   186.9 1926.18   236.1 1908.45
   265.6 1896.22   275.4 1888.87   314.8 1865.82   354.1 1839.81   373.8 1820.96
   403.3 1801.91   442.6 1779.02   462.3 1763.81   491.8 1751.23   533.5 1741.81
     541 1740.16   548.5 1742.74   570.7 1750.56   620.2 1761.22   630.1 1764.93
   699.4  1781.6   709.3 1786.61   719.2 1789.23     848 1810.94   897.5 1822.37
   956.9 1840.99  1016.3 1856.24  1036.1 1864.22  1095.5 1883.01  1115.3 1892.65
#Mann= 3 , 0 , 0
       0     .06       0   533.5    .045       0   548.5     .06       0
Bank Sta=533.5,548.5
XS Rating Curve= 0 ,0
Exp/Cntr=0.3,0.1

Type RM Length L Ch R = 1 ,5362.9  ,409.4,371.1,331.9
XS GIS Cut Line= 3
      1886014.77      233563.165     1885355.521      233314.524
     1885104.652      233347.171
#Sta/Elev= 30
       0 1802.16    29.8 1801.45    89.3 1795.41   119.1 1794.49     129 1794.35
   158.8 1799.15   188.6  1796.3   238.2 1801.88   277.9 1798.18   367.2  1782.1
   416.8 1764.05   456.5 1751.96   476.3 1749.09   523.2 1732.21   535.9 1731.26
   538.2 1732.37   565.6  1744.1   595.4 1753.64   694.7 1760.25     724 1764.32
   811.6 1771.48   831.1    1774   850.5 1778.13   860.3 1781.22     870 1786.08
   879.7 1793.98   908.9 1806.79   928.4 1817.01   947.8 1828.47   957.6 1840.08
#Mann= 3 , 0 , 0
       0     .06       0   523.2    .045       0   538.2     .06       0
Bank Sta=523.2,538.2
XS Rating Curve= 0 ,0
Exp/Cntr=0.3,0.1

Type RM Length L Ch R = 1 ,4991.8  ,281,311.3,342.1
XS GIS Cut Line= 4
     1885953.324      233029.586     1885496.829      233017.001
     1885421.155      233222.635     1885104.652      233347.171
#Sta/Elev= 30
       0 1850.99    39.7 1833.84    49.6  1828.6    59.6 1818.01    79.4 1808.97
   129.1 1793.04     139 1787.45   208.5  1769.7   218.4  1764.8   258.1 1754.96
     278 1751.84   307.8 1749.89   456.7 1745.26   536.4 1744.53   576.2 1738.71
   586.2 1733.62   592.4 1731.84   596.1 1730.78   607.4 1733.16   645.9 1747.31
   665.8 1751.25   715.8 1752.24   765.8 1755.46   795.8 1758.73   885.9  1772.3
   915.9 1782.19   935.9 1797.01   975.9 1814.36  1005.9 1829.19  1015.9 1840.08
#Mann= 3 , 0 , 0
       0     .06       0   592.4    .045       0   607.4     .06       0
Bank Sta=592.4,607.4
XS Rating Curve= 0 ,0
Exp/Cntr=0.3,0.1

Type RM Length L Ch R = 1 ,4680.6  ,87,86.9,86.2
XS GIS Cut Line= 3
     1885541.486      232944.781     1885330.446      232926.466
     1884801.605       232868.53
#Sta/Elev= 30
       0 1746.07    57.8 1742.99   134.8  1741.1   154.1 1737.24   173.3 1731.12
     183 1728.95   202.2  1728.3   204.3  1728.3   219.3  1728.3   251.2 1728.78
   261.1 1730.34   270.9  1732.9   280.8 1736.48   290.6  1742.2   359.6  1765.4
   369.5 1771.84   438.4 1793.04   448.3 1798.79   458.1 1802.31   517.2 1820.08
   527.1 1825.22     537 1829.36   596.1 1847.02   615.8 1855.86   674.9 1872.48
   684.7 1876.08   694.6 1880.72   724.1 1888.46     734 1890.37   743.8 1890.59
#Mann= 3 , 0 , 0
       0     .06       0   204.3    .045       0   219.3     .06       0
Bank Sta=204.3,219.3
XS Rating Curve= 0 ,0
Exp/Cntr=0.3,0.1

Type RM Length L Ch R = 1 ,4593.7  ,49.8,49,48.2
XS GIS Cut Line= 2
     1885847.443      232880.767     1884839.607      232800.079
#Sta/Elev= 30
       0 1846.75    99.1 1824.42     119 1816.62   178.4  1799.5   218.1 1782.86
   267.6  1750.9   277.6 1745.76     337 1732.75   356.8 1724.58   376.7 1722.34
   406.4  1725.5   426.2 1731.63   436.1 1737.04   446.1 1738.73     456 1738.41
   495.6 1728.69   504.8 1728.29   519.8  1728.3   555.1 1728.57   584.8 1733.59
   634.4 1747.99     674 1761.43   743.4 1775.94   763.2 1783.44   822.7 1799.93
   842.6 1809.71     902  1829.3   921.8 1838.69   981.3 1854.68  1011.1 1864.81
#Mann= 3 , 0 , 0
       0     .06       0   504.8    .045       0   519.8     .06       0
#XS Ineff= 2 , 0
          445.19 1750.92
Permanent Ineff=
       F       F
Bank Sta=504.8,519.8
XS Rating Curve= 0 ,0
Exp/Cntr=0.3,0.1

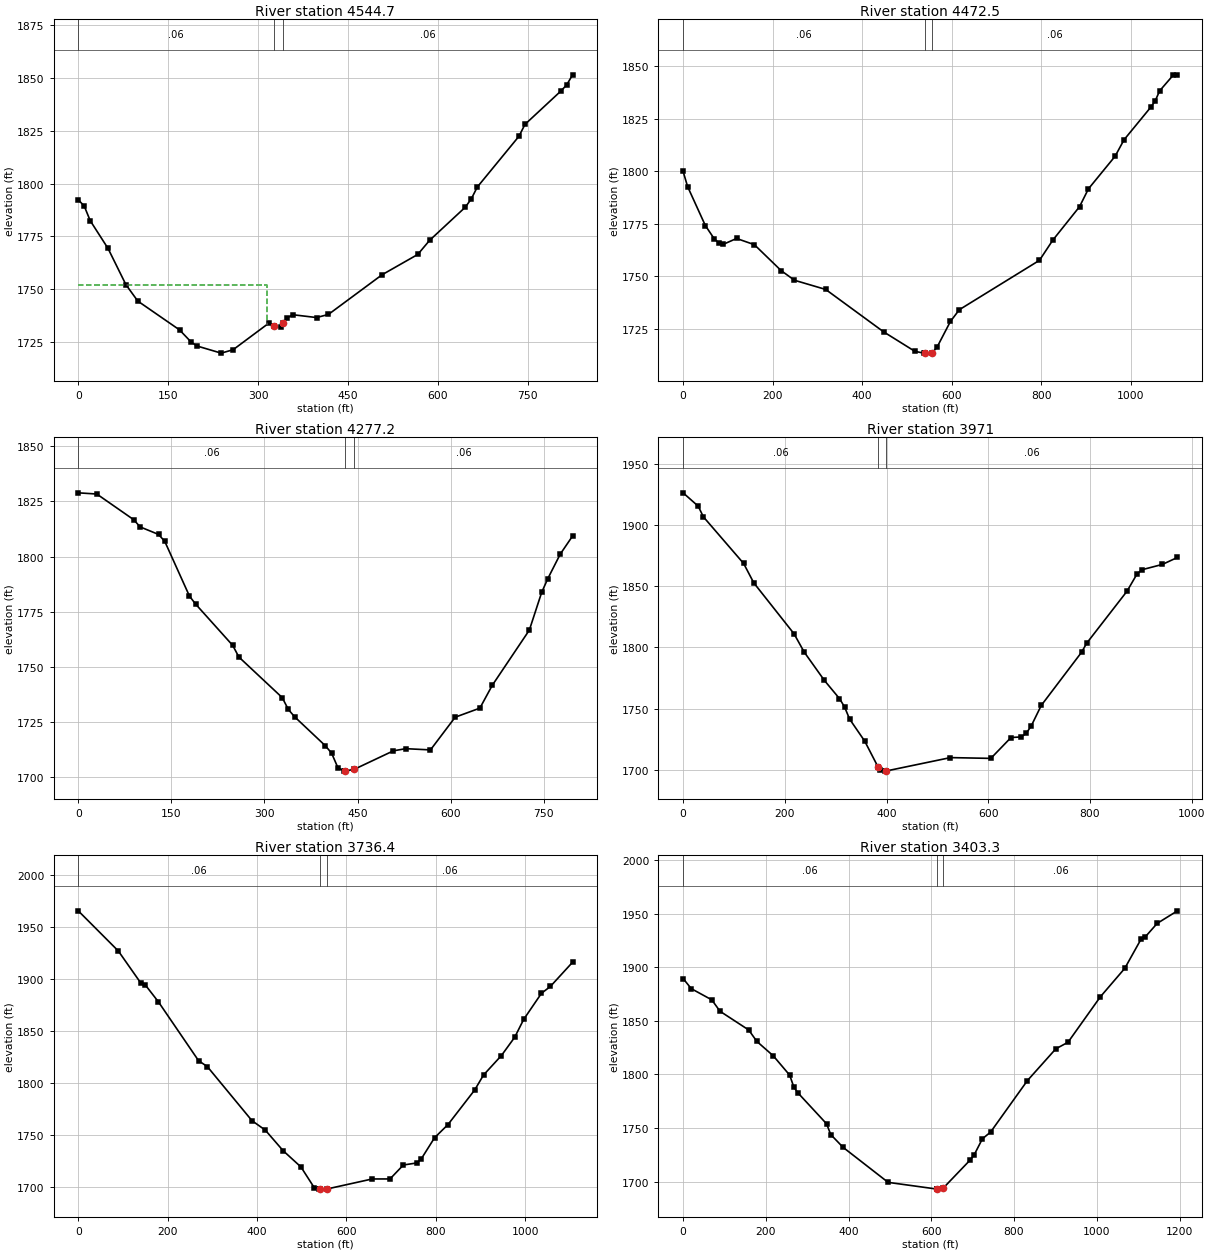
Type RM Length L Ch R = 1 ,4544.7  ,72.7,72.2,71.6
XS GIS Cut Line= 2
     1885675.764      232806.717     1884852.078      232768.765
#Sta/Elev= 30
       0 1792.26     9.9 1789.35    19.9 1782.38    49.7 1769.17    79.5    1752
    99.3 1744.22   168.9 1730.55   188.8 1724.63   198.7 1722.85   238.4 1719.52
   258.3 1721.13   317.9 1733.75   326.7 1732.16   337.8    1732   341.7 1733.58
   347.7 1736.02   357.6 1737.75   397.4  1736.4   417.2 1737.86   506.7 1756.69
   566.3 1766.34   586.1 1773.04   645.7 1788.78   655.7 1792.76   665.6 1798.31
   735.2 1822.44   745.1 1828.04   804.7 1843.78   814.6 1846.74   824.6 1851.56
#Mann= 3 , 0 , 0
       0     .06       0   326.7    .045       0   341.7     .06       0
#XS Ineff= 2 , 0
           314.5 1751.63
Permanent Ineff=
       F       F
Bank Sta=326.7,341.7
XS Rating Curve= 0 ,0
Exp/Cntr=0.3,0.1

Type RM Length L Ch R = 1 ,4472.5  ,195.3,195.2,195.2
XS GIS Cut Line= 3
     1885905.778      232732.893     1885348.774      232720.601
     1884802.177      232714.439
#Sta/Elev= 30
       0 1799.84      10 1792.62    49.7 1774.03    69.6  1767.7    79.6 1765.79
    89.5 1765.08   119.4 1767.89   159.2 1764.92   218.9 1752.58   248.7 1747.98
   318.4  1743.6   447.7 1723.41   517.3 1714.15   537.2 1713.27   541.2  1713.3
   556.2 1713.39   567.1 1716.14   596.9 1728.37   616.8 1733.96   795.7 1757.48
   825.5  1767.1   885.1 1783.01     905 1791.52   964.6 1807.06   984.5 1814.89
  1044.1 1830.39  1054.1 1833.42    1064  1838.2  1093.8 1845.56  1103.8 1845.84
#Mann= 3 , 0 , 0
       0     .06       0   541.2    .045       0   556.2     .06       0
Bank Sta=541.2,556.2
XS Rating Curve= 0 ,0
Exp/Cntr=0.3,0.1

Type RM Length L Ch R = 1 ,4277.2  ,319.7,306.3,292.8
XS GIS Cut Line= 2
     1885823.715      232535.658     1885027.347      232522.531
#Sta/Elev= 30
       0 1828.93    29.9 1828.38    89.6 1816.67    99.6 1813.46   129.4 1810.02
   139.4 1806.86   179.2    1782   189.2 1778.34   248.9  1759.6   258.8 1754.33
   328.6 1735.91   338.5 1730.51   348.5 1727.21   398.2    1714   408.2 1710.66
   418.2 1704.13   428.1  1702.5   429.8 1702.53   444.8 1703.34   507.8 1711.73
   527.7  1712.7   567.5 1712.14   607.3    1727   647.1 1731.12     667 1741.46
   726.8 1766.58   746.7 1783.75   756.6 1789.99   776.6 1801.09   796.5 1809.34
#Mann= 3 , 0 , 0
       0     .06       0   429.8    .045       0   444.8     .06       0
Bank Sta=429.8,444.8
XS Rating Curve= 0 ,0
Exp/Cntr=0.3,0.1

Type RM Length L Ch R = 1 ,3971    ,238.8,234.6,230.3
XS GIS Cut Line= 2
      1885668.38      232023.706     1884854.508      232555.348
#Sta/Elev= 30
       0 1926.28    29.8 1915.34    39.7 1906.75     119 1868.58   138.9 1852.78
   218.2 1811.08   238.1 1796.19   277.8 1773.03   307.5 1758.18   317.4 1751.43
   327.4 1741.44   357.1 1723.44   383.8 1701.94   386.9 1699.99   396.8 1698.92
   398.8 1698.99   525.7 1709.97   605.1 1709.33   644.8 1726.38   664.6 1726.84
   674.5 1729.68   684.5 1735.78   704.3 1752.61   783.6 1796.07   793.6 1803.43
   872.9  1845.9   892.8 1860.13   902.7 1863.49   942.4 1867.79   972.1 1873.49
#Mann= 3 , 0 , 0
       0     .06       0   383.8    .045       0   398.8     .06       0
Bank Sta=383.8,398.8
XS Rating Curve= 0 ,0
Exp/Cntr=0.3,0.1

Type RM Length L Ch R = 1 ,3736.4  ,326.7,333,339.3
XS GIS Cut Line= 2
     1885561.731      231701.778     1884764.448      232468.634
#Sta/Elev= 30
       0 1965.87    89.7  1927.2   139.5 1896.66   149.5 1894.85   179.4 1878.25
   269.1 1821.73     289 1815.87   388.7 1763.95   418.6 1754.81   458.4 1735.05
   498.3  1719.4   528.2 1699.36   538.2 1698.06   540.7 1698.07   555.7 1698.12
   657.8 1707.84   697.6 1707.86   727.5 1721.28   757.4 1723.24   767.4 1727.06
   797.3 1747.52   827.2 1760.13     887 1793.41   906.9 1807.89   946.8 1826.56
   976.7 1844.25   996.6  1861.3  1036.5  1886.5  1056.4 1893.07  1106.2 1916.44
#Mann= 3 , 0 , 0
       0     .06       0   540.7    .045       0   555.7     .06       0
Bank Sta=540.7,555.7
XS Rating Curve= 0 ,0
Exp/Cntr=0.3,0.1

Type RM Length L Ch R = 1 ,3403.3  ,224.5,233.3,242.2
XS GIS Cut Line= 3
     1885460.377      231595.715     1884740.741      231973.386
      1884597.22      232327.717
#Sta/Elev= 30
       0 1889.53    19.8 1880.04    69.4  1869.6    89.2 1858.97   158.6  1841.5
   178.4 1830.79     218 1817.37   257.7 1799.32   267.6 1788.27   277.5 1782.82
   346.9  1753.9   356.8 1743.96   386.5 1732.05   495.6  1699.3   613.9 1693.02
   614.5 1692.99   628.9 1693.98   693.8 1720.11   703.7 1725.05   723.5 1739.96
   743.3 1746.24   832.3 1794.28   900.9 1823.89   930.4 1830.02  1008.8 1872.53
  1067.6 1898.98  1106.8 1926.11  1116.6 1928.11    1146 1940.96    1195 1952.68
#Mann= 3 , 0 , 0
       0     .06       0   613.9    .045       0   628.9     .06       0
Bank Sta=613.9,628.9
XS Rating Curve= 0 ,0
Exp/Cntr=0.3,0.1

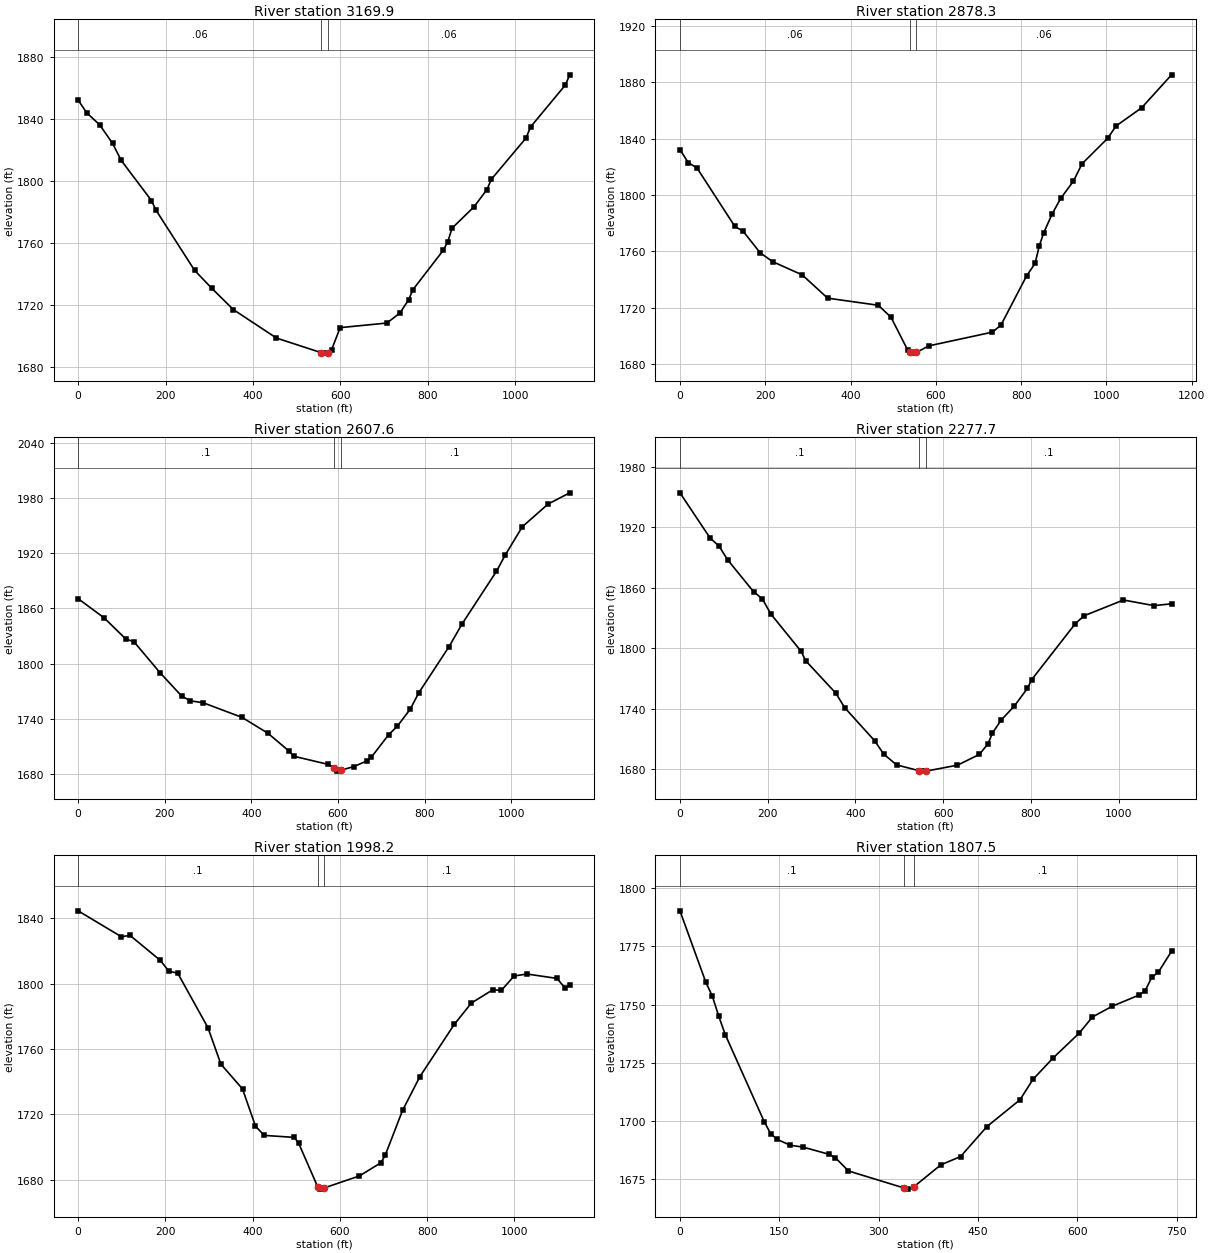
Type RM Length L Ch R = 1 ,3169.9  ,311.6,291.2,270.7
XS GIS Cut Line= 4
     1885377.809      231488.304      1884967.03      231656.287
     1884696.028      231679.055     1884333.915       231868.15
#Sta/Elev= 30
       0 1852.13    19.7 1843.93    49.3 1836.19    78.9 1824.18    98.6 1813.26
   167.7 1787.45   177.5 1781.51   266.3 1742.53   305.7 1730.96     355 1717.25
   453.5 1698.94   555.4 1689.56   560.4 1689.22   570.4 1689.39   579.8 1691.45
   599.2 1705.62     706 1708.59   735.7 1714.93   755.6 1723.42   765.6 1730.06
   835.3 1755.48   845.3 1760.89   855.2 1769.66   905.1 1783.32     935  1794.5
   944.9 1801.07  1024.6 1827.78  1034.6 1834.78  1114.3 1861.81  1124.3 1868.37
#Mann= 3 , 0 , 0
       0     .06       0   555.4    .045       0   570.4     .06       0
Bank Sta=555.4,570.4
XS Rating Curve= 0 ,0
Exp/Cntr=0.3,0.1

Type RM Length L Ch R = 1 ,2878.3  ,263.2,270.7,278.3
XS GIS Cut Line= 3
     1885087.082      230997.138     1884698.489      231558.451
      1884300.09      231807.774
#Sta/Elev= 30
       0 1832.34    19.8 1822.99    39.6 1819.47   128.6 1777.87   148.4 1774.29
     188  1759.1   217.7 1752.74   286.9 1743.35   346.3 1726.87     465 1721.82
   494.7 1713.42   534.3 1689.82     539 1688.88   544.2 1687.84     554 1688.29
   583.8 1693.01   732.7 1702.75   752.7 1707.73   812.7 1742.62   832.7 1751.56
   842.7 1764.11   852.7 1773.07   872.7 1786.66   892.7 1797.68   922.7 1809.99
   942.7 1822.24  1002.7 1840.31  1022.7 1849.14  1082.7 1862.07  1152.7 1885.44
#Mann= 3 , 0 , 0
       0     .06       0     539    .045       0     554     .06       0
Bank Sta=539,554
XS Rating Curve= 0 ,0
Exp/Cntr=0.3,0.1

Type RM Length L Ch R = 1 ,2607.6  ,323.9,329.7,333.3
XS GIS Cut Line= 2
     1885034.637      230949.829     1884120.493      231622.207
#Sta/Elev= 30
       0 1870.44    59.7 1849.68   109.5 1826.89   129.4 1823.36   189.1 1789.98
   238.9  1764.7   258.8 1759.48   288.7 1757.35   378.3 1741.46     438 1724.29
   487.8 1704.47   497.7 1699.27   577.4 1690.37     591 1686.21   597.3 1683.08
     606 1684.03   637.1 1688.09   666.9 1694.29   676.9 1698.19   716.7  1722.6
   736.6 1731.72   766.5 1750.29   786.4 1768.19   856.1 1818.19   885.9 1842.69
   965.6 1900.08   985.5 1917.47  1025.3 1948.51    1085 1973.29  1134.8 1985.41
#Mann= 3 , 0 , 0
       0      .1       0     591    .045       0     606      .1       0
Bank Sta=591,606
XS Rating Curve= 0 ,0
Exp/Cntr=0.3,0.1

Type RM Length L Ch R = 1 ,2277.7  ,291.8,279.4,269.3
XS GIS Cut Line= 3
     1884970.279      230799.448     1884455.553      231001.799
     1883950.165       231260.15
#Sta/Elev= 30
       0 1954.25    69.1 1909.15    88.9 1901.49   108.6 1887.77   167.9    1856
   187.6  1849.1   207.4 1833.78   276.5 1796.67   286.4  1787.6   355.6 1755.17
   375.3 1741.02   444.4 1707.73   464.2 1694.93   493.8 1684.06   545.6 1678.22
   553.1 1677.86   560.6 1677.86   632.7 1683.77   682.5 1694.42   702.4 1705.04
   712.4 1715.69   732.3 1728.54   762.2 1742.46   792.1    1760     802 1768.82
   901.6 1824.47   921.5 1832.18  1011.1  1847.8  1080.8 1842.23  1120.7 1844.02
#Mann= 3 , 0 , 0
       0      .1       0   545.6    .045       0   560.6      .1       0
Bank Sta=545.6,560.6
XS Rating Curve= 0 ,0
Exp/Cntr=0.3,0.1

Type RM Length L Ch R = 1 ,1998.2  ,181.1,190.8,199.8
XS GIS Cut Line= 3
     1884647.173      230358.333     1884147.157      230999.735
     1883901.799      231195.228
#Sta/Elev= 30
       0 1844.55    99.2 1828.68     119 1829.51   188.4  1814.2   208.3 1807.51
   228.1 1806.45   297.5 1773.06   327.3 1750.66   376.9 1735.45   406.6 1712.69
   426.5 1707.03   495.9 1705.79   505.8 1702.08   549.1 1675.58   555.4 1674.12
   564.1 1674.84   644.7 1682.18   694.3 1690.29   704.2 1695.01   743.8 1722.35
   783.5 1743.02   862.3 1774.99   901.5 1788.07   950.5 1796.18   970.1 1795.78
   999.5 1804.64    1029 1805.85  1097.6 1803.17  1117.2 1797.08    1127 1799.22
#Mann= 3 , 0 , 0
       0      .1       0   549.1    .045       0   564.1      .1       0
Bank Sta=549.1,564.1
XS Rating Curve= 0 ,0
Exp/Cntr=0.3,0.1

Type RM Length L Ch R = 1 ,1807.5  ,163.1,163.5,164.4
XS GIS Cut Line= 3
     1884421.592       230498.86     1884229.611       230650.23
     1883796.421       230895.13
#Sta/Elev= 30
       0 1790.24    39.1 1759.58    48.9 1753.62    58.7 1744.94    68.4 1737.14
   127.1 1699.86   136.9 1694.66   146.7 1692.22   166.2  1689.7   185.8 1688.88
   224.9  1685.8   234.7 1684.31   254.4 1678.64   338.6 1671.31     344 1670.85
   353.6 1671.97   393.8 1681.26   423.6 1684.82   463.4 1697.69   513.2 1709.15
   533.1 1717.99     563 1727.03   602.8  1737.8   622.7 1744.71   652.5  1749.3
   692.3 1754.01   702.3 1755.96   712.2 1761.74   722.2 1763.91   742.1 1772.93
#Mann= 3 , 0 , 0
       0      .1       0   338.6    .045       0   353.6      .1       0
Bank Sta=338.6,353.6
XS Rating Curve= 0 ,0
Exp/Cntr=0.3,0.1

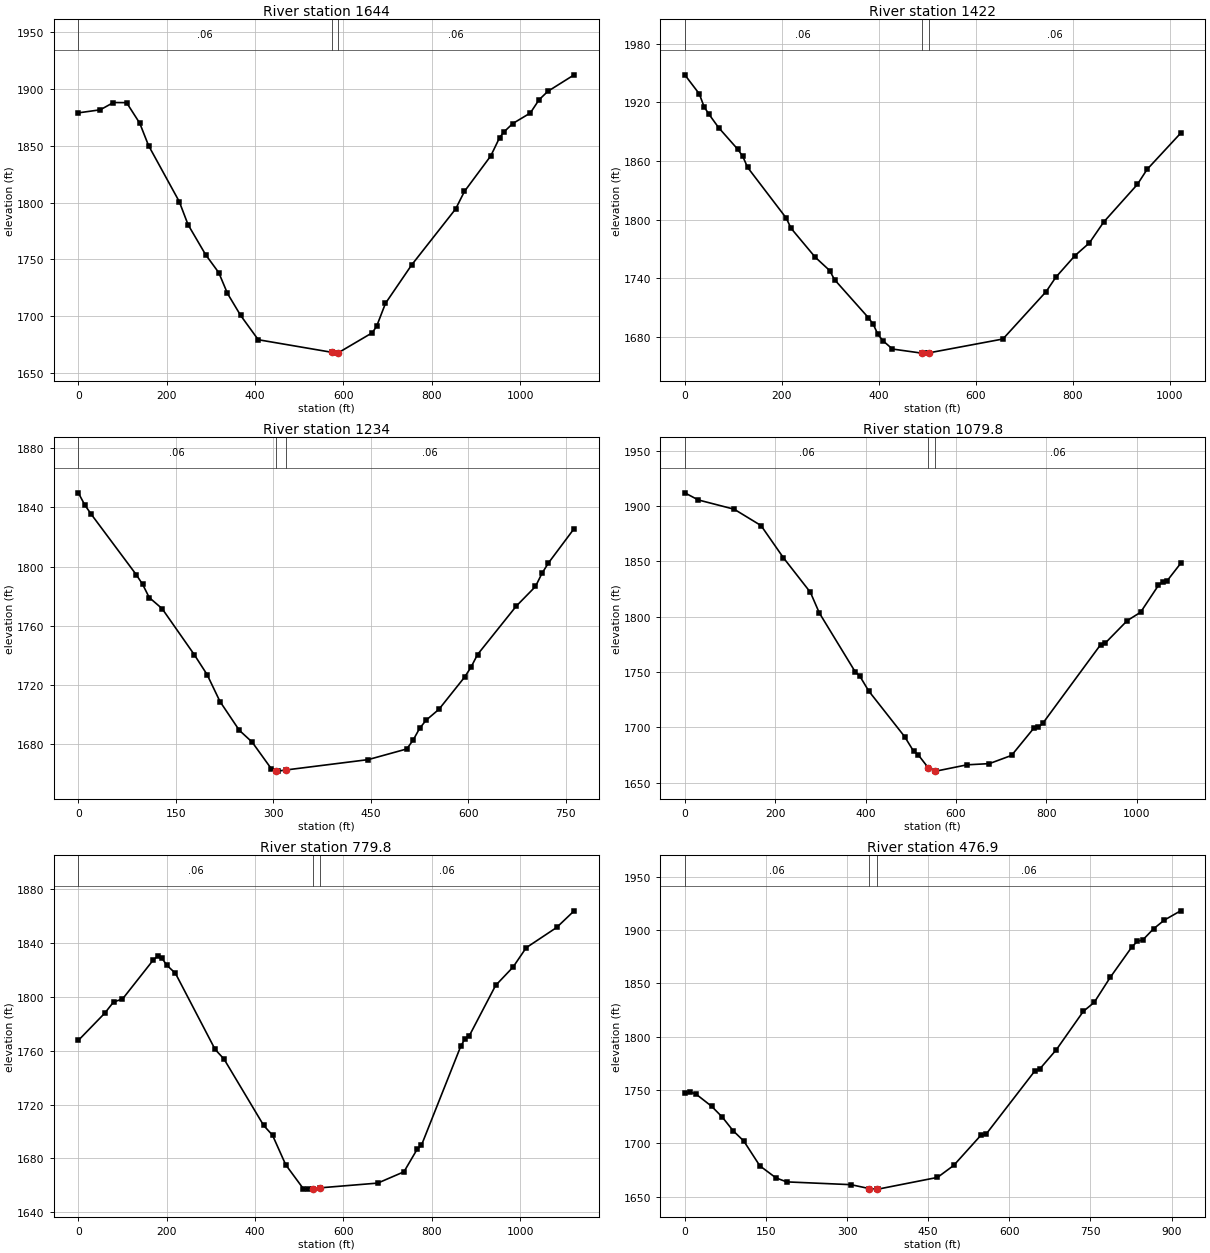
Type RM Length L Ch R = 1 ,1644    ,224.6,222.1,219.6
XS GIS Cut Line= 2
     1884592.659      230294.702     1883589.062      230796.773
#Sta/Elev= 30
       0 1879.09    49.6 1881.78    79.4  1888.2   109.2  1888.1     139 1869.97
   158.9 1850.26   228.4 1800.87   248.3 1780.52     288 1754.08   317.8 1738.21
   337.6 1719.81   367.4 1700.41   407.2 1679.02   573.2 1667.96   585.9  1667.2
   588.2 1667.48   665.4 1685.19   675.3 1691.04   695.2 1711.13   754.7 1745.13
     854 1794.38   873.9 1809.82   933.5 1841.13   953.4 1857.22   963.3 1862.26
   983.2 1869.66  1022.9 1878.93  1042.7  1890.6  1062.6 1898.06  1122.2 1912.63
#Mann= 3 , 0 , 0
       0     .06       0   573.2    .045       0   588.2     .06       0
Bank Sta=573.2,588.2
XS Rating Curve= 0 ,0
Exp/Cntr=0.3,0.1

Type RM Length L Ch R = 1 ,1422    ,190.5,187.8,185
XS GIS Cut Line= 3
     1884479.433      230113.666      1884095.47      230303.186
     1883590.902      230617.003
#Sta/Elev= 30
       0 1948.05    29.9 1928.57    39.8 1915.35    49.8 1907.76    69.7 1894.09
   109.5 1871.75   119.5 1864.74   129.4 1853.46   209.1 1801.63   219.1 1791.14
   268.9  1761.6   298.7 1747.96   308.7 1738.66   378.4 1699.84   388.4 1693.16
   398.3 1682.61   408.3 1676.28   428.2 1667.69   488.1 1663.53   497.5 1663.51
   503.1 1663.76     656 1677.95   745.1 1726.41   764.9    1741   804.5 1763.19
   834.2 1776.16   863.9  1797.6   933.3 1836.05   953.1 1851.28  1022.4 1888.36
#Mann= 3 , 0 , 0
       0     .06       0   488.1    .045       0   503.1     .06       0
Bank Sta=488.1,503.1
XS Rating Curve= 0 ,0
Exp/Cntr=0.3,0.1

Type RM Length L Ch R = 1 ,1234    ,156.8,154.4,153.2
XS GIS Cut Line= 2
     1884207.459      229975.833     1883616.746      230458.249
#Sta/Elev= 30
       0 1849.89     9.9 1841.71    19.8 1835.44    89.1 1794.59      99    1788
     109 1779.17   128.8 1771.69   178.3  1740.6   198.1 1727.08   217.9 1708.91
   247.6 1689.47   267.4 1681.47   297.1 1663.34   304.3 1662.28     307 1661.88
   319.3 1662.66   445.7 1669.64   505.2 1676.86     515 1682.84     525 1690.77
   534.9 1696.25   554.7 1703.64   594.3 1725.45   604.2 1732.22   614.1 1740.66
   673.5 1773.28   703.2 1786.61   713.2 1795.49     723 1802.42   762.7 1825.74
#Mann= 3 , 0 , 0
       0     .06       0   304.3    .045       0   319.3     .06       0
Bank Sta=304.3,319.3
XS Rating Curve= 0 ,0
Exp/Cntr=0.3,0.1

Type RM Length L Ch R = 1 ,1079.8  ,304,299.8,294.5
XS GIS Cut Line= 3
     1884240.259      229675.589     1883856.966      230064.218
     1883449.298        230435.3
#Sta/Elev= 30
       0 1911.79    29.8 1905.37   109.2    1897   168.7 1882.22   218.3 1853.11
   277.9 1821.96   297.7  1803.3   377.1 1750.15     387 1746.48   406.9 1732.91
   486.3 1691.72   506.2 1678.53   516.1 1675.42   538.3 1663.74   553.3 1660.62
   555.7 1660.51   624.6 1666.21   673.8 1667.28     723  1674.7   772.3 1699.34
   782.1 1700.07     792 1703.61   919.9  1774.6   929.8  1775.9     979 1796.41
  1008.5 1803.95  1047.9 1828.18  1057.7 1831.72  1067.6 1832.55  1097.1 1848.04
#Mann= 3 , 0 , 0
       0     .06       0   538.3    .045       0   553.3     .06       0
Bank Sta=538.3,553.3
XS Rating Curve= 0 ,0
Exp/Cntr=0.3,0.1

Type RM Length L Ch R = 1 ,779.8   ,311,302.5,294.1
XS GIS Cut Line= 3
     1883972.993      229396.467     1883667.381      229841.028
     1883336.845      230321.241
#Sta/Elev= 30
       0 1767.64    59.9 1787.88    79.9 1796.21    99.9 1798.31   169.8  1827.4
   179.8 1830.23   189.8 1828.48   199.8  1823.6   219.8 1817.44   309.7  1760.9
   329.7 1753.83   419.6 1704.48   439.6 1697.24   469.5 1675.28   509.5 1657.47
   519.5 1657.22     532 1657.68     547 1658.17   677.8  1661.7   737.1 1670.08
   766.7 1686.66   776.6 1689.69   865.6 1763.22   875.4 1768.91   885.3 1771.22
   944.6 1808.44   984.1 1822.06  1013.8 1836.43  1082.9  1851.5  1122.4 1863.83
#Mann= 3 , 0 , 0
       0     .06       0     532    .045       0     547     .06       0
Bank Sta=532,547
XS Rating Curve= 0 ,0
Exp/Cntr=0.3,0.1

Type RM Length L Ch R = 1 ,476.9   ,293.9,296.8,298.6
XS GIS Cut Line= 3
      1883643.82      229493.417     1883406.304      229703.859
     1883260.549      230285.257
#Sta/Elev= 30
       0 1746.74     9.9 1747.95    19.8 1746.52    49.6 1734.69    69.4 1724.52
    89.2 1711.85   109.1 1702.09   138.8 1678.82   168.6 1667.52   188.4  1663.8
   307.4 1661.18     341 1657.51     356 1657.01   357.3    1657   467.2    1668
   497.2 1679.25   547.1 1707.34   557.1 1708.61     647 1767.75     657 1770.13
     687 1787.83   736.9 1823.82   756.9 1832.15   786.8 1855.82   826.8 1884.35
   836.8 1889.46   846.8  1890.8   866.8 1901.28   886.8 1909.44   916.7 1918.07
#Mann= 3 , 0 , 0
       0     .06       0     341    .045       0     356     .06       0
Bank Sta=341,356
XS Rating Curve= 0 ,0
Exp/Cntr=0.3,0.1

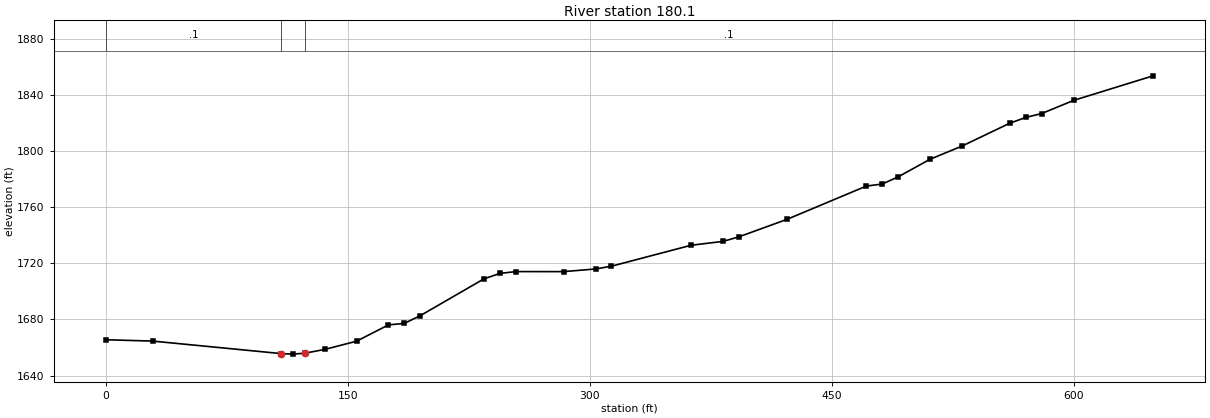
Type RM Length L Ch R = 1 ,180.1   ,161.5,180.1,199.8
XS GIS Cut Line= 3
     1883160.174      229569.718     1883118.325      229677.799
     1882949.659      230183.869
#Sta/Elev= 30
       0 1665.53      29 1664.58   108.4  1655.7   115.9 1655.29   123.4 1655.96
   135.7 1658.64   155.4 1664.49   175.2 1676.12     185 1677.16   194.9 1682.67
   234.4 1708.89   244.3 1712.78   254.2 1714.08   283.8 1714.06   303.6 1715.94
   313.5 1717.93   362.9 1732.85   382.6 1735.58   392.5 1738.84   422.1 1751.19
   471.5 1774.98   481.4 1776.46   491.3  1781.6     511 1794.09   530.8 1803.47
   560.4 1819.73   570.3 1823.87   580.2 1826.63     600 1836.01   649.3 1853.52
#Mann= 3 , 0 , 0
       0      .1       0   108.4    .045       0   123.4      .1       0
Bank Sta=108.4,123.4
XS Rating Curve= 0 ,0
Exp/Cntr=0.3,0.1

Chan Stop Cuts=-1
Use User Specified Reach Order=0
Composite Channel Slope=5